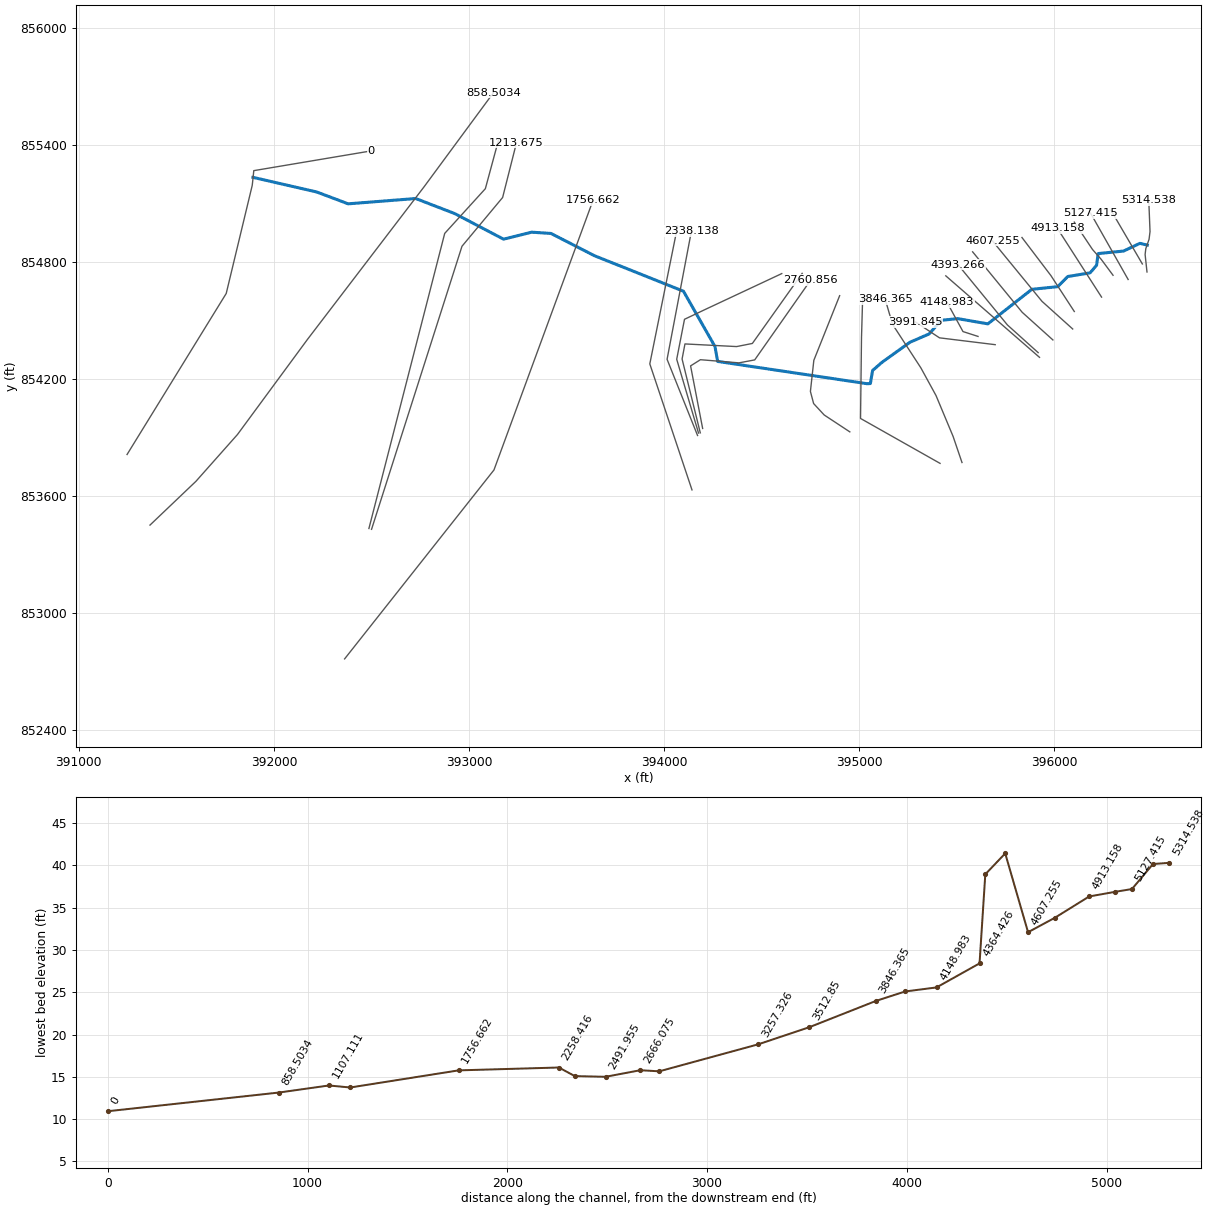
--- 6978_ras.prj (project) ---

Proj Title=6978
Current Plan=p01
Default Exp/Contr=0.3,0.1
English Units
Geom File=g01
Flow File=f01
Plan File=p01
Y Axis Title=Elevation
X Axis Title(PF)=Main Channel Distance
X Axis Title(XS)=Station
BEGIN DESCRIPTION:
RFD model 6978 exported to HEC-RAS
END DESCRIPTION:

--- 6978_ras.p01 (plan) ---

Plan Title=Plan 01
Program Version=4.10
Short Identifier=Plan 01
Geom File=g01
Flow File=f01
Subcritical Flow
Calc Critical at every XS
Secant Critical Depth

--- 6978_ras.f01 (steady flow) ---

Flow Title=Flow 01
Program Version=5.01
Number of Profiles= 6
Profile Names=10yr,25yr,50yr,100yr,100plus,500yr
River Rch & RM=6978,25,5314.538
  147.09  236.22  319.61  396.21  578.46 1029.82
River Rch & RM=6978,25, 5043.98
  152.32  244.69  331.14  410.57  599.43 1062.09
River Rch & RM=6978,25,4913.158
  157.51   253.1  342.59  424.82  620.24 1093.99
River Rch & RM=6978,25,4741.453
  162.67  261.45  353.96  438.98  640.92 1125.52
River Rch & RM=6978,25,4607.255
     167  268.47  363.53   450.9  658.31 1151.94
River Rch & RM=6978,25, 4492.96
  168.57  271.01  366.99  455.21  664.61 1161.48
River Rch & RM=6978,25,4393.266
   171.3  275.44  373.03  462.73  675.59 1178.12
River Rch & RM=6978,25,4148.983
  173.99  279.81     379  470.19  686.48 1194.66
River Rch & RM=6978,25,3991.845
  217.15   349.7  474.18  588.65  859.42  1450.6
River Rch & RM=6978,25,3846.365
  219.69  353.84  479.85  595.73  869.77 1465.86
River Rch & RM=6978,25, 3512.85
  229.05  369.13  500.78  621.91  907.99 1521.98
River Rch & RM=6978,25,3257.326
  231.91   373.8  507.19  629.92  919.69 1539.08
River Rch & RM=6978,25,2760.856
  250.34  403.91  548.42   681.5  994.99 1648.51
Boundary for River Rch & Prof#=6978,25,1
Up Type= 0
Dn Type= 2
Boundary for River Rch & Prof#=6978,25,2
Up Type= 0
Dn Type= 2
Boundary for River Rch & Prof#=6978,25,2
Up Type= 0
Dn Type= 2
Boundary for River Rch & Prof#=6978,25,2
Up Type= 0
Dn Type= 2
Boundary for River Rch & Prof#=6978,25,2
Up Type= 0
Dn Type= 2
Boundary for River Rch & Prof#=6978,25,2
Up Type= 0
Dn Type= 2

--- 6978_ras.g01 (geometry) ---

Geom Title=6978
Program Version=4.10

River Reach=6978,25
Reach XY= 30
396477.078090549854887.343144611396438.883645952854896.370922402
396355.203090459854856.787589073396224.994757056854843.940366864
396217.008646101854784.218144611396183.675312608854744.982033491
396069.091979295854726.232033491396017.355868191854674.148700163
395885.064201593854660.607033491395659.716979295854483.523700163
  395505.2030904854510.259811297395420.642905354854501.625552028
395358.663738549854431.833885357395260.573460907854389.299163148
395116.476238698854286.000552028395068.733182997854244.333885372
395057.448460847854177.493607581395040.955405205854176.625552043
394274.586962998854290.858177334394261.066082299854366.553214058
 394099.39073506854650.841408521393642.576498955854833.133075178
393420.137262851854947.065366849393321.395943403854953.575783506
393177.081707418854917.768491834392926.430665612855049.061894625
392726.777887851855126.101825163 392380.64073512855098.975089058
 392218.96538806855159.738977939391892.305008292855234.808035955

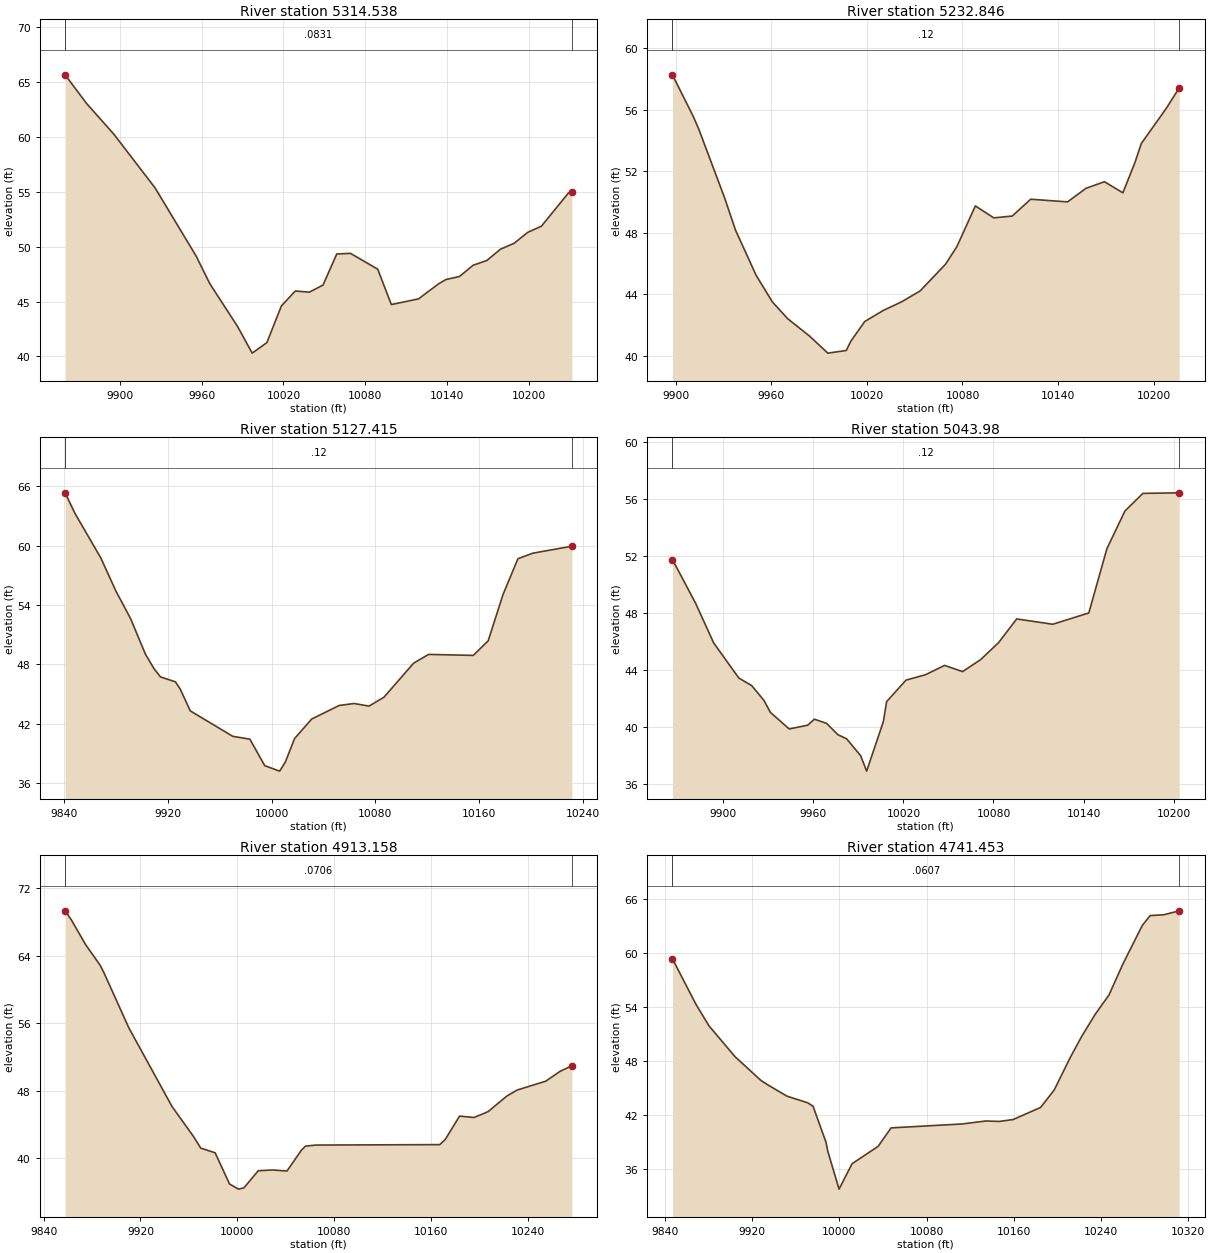
Type RM Length L Ch R = 1 ,5314.538,81.691900,81.691900,81.691900
XS GIS Cut Line= 6
396475.379451826854749.516391192396465.737836073854839.268064045
396469.329940503854869.121088094396486.017077459854917.471304507
396490.937346516854956.611074324396484.504310328855117.318750072
#Sta/Elev= 30
9859.68465.640459875.33963.04599 9895.5660.222299925.75955.337589955.83149.14895
9965.903 46.62669986.377 42.7134 9997.0140.3023810007.8341.2645110018.4344.58974
10027.45 45.799510028.7945.9590710038.94 45.851810049.0246.49814 10059.149.32857
10069.1749.3859310089.1947.9454810099.1944.7217210119.1945.2439610133.7846.60261
 10139.246.9979810149.23 47.281310159.25 48.305310169.2848.73547 10179.3 49.7637
10189.3350.3029610199.3551.3006810209.3851.8617410229.4254.9147510231.7554.98514
#Mann= 3 , 0 , 0
9859.684  0.0831       09859.684  0.0831       010231.75  0.0831       0
#XS Ineff= 2 , 0
       0                               0
Bank Sta=9859.684,10231.75
Exp/Cntr=0.3,0.1

Type RM Length L Ch R = 1 ,5232.846,105.431100,105.431100,105.431100
XS GIS Cut Line= 2
 396451.54848251854790.739688065396290.957090044855065.555679741
#Sta/Elev= 30
9897.83558.261289910.81555.575869914.35254.737019930.63550.249529937.51648.14607
9950.45545.212229960.68143.482999970.27642.396939983.84541.281379995.42740.16378
10007.01 40.335410009.9240.9488610018.5942.2164710030.1742.9341410041.7643.50081
10053.3444.2037710069.3845.94908 10076.547.0927910088.0949.7359310099.6748.95934
10111.2549.0782810122.83 50.1719   1014649.9987510157.5850.8822110169.1651.31033
10180.7450.58942 10188.352.5529510192.3353.7964210208.1256.0992910216.1357.41341
#Mann= 3 , 0 , 0
9897.835    0.12       09897.835    0.12       010216.13    0.12       0
#XS Ineff= 2 , 0
       0                               0
Bank Sta=9897.835,10216.13
Exp/Cntr=0.3,0.1

Type RM Length L Ch R = 1 ,5127.415,83.435500,83.435500,83.435500
XS GIS Cut Line= 2
396378.762024172854710.965382483396186.053690824 855051.24316026
#Sta/Elev= 30
9840.706  65.333 9848.3463.248129868.32758.729589879.81955.426029891.31152.59318
9902.80448.989649909.21847.578559914.29646.726079925.78846.23183 9929.5145.50159
 9937.2843.293769970.09640.71947 9983.2540.436429994.74237.7530410006.2337.20391
10010.6838.1364310017.7340.4929210030.9742.46921 10052.243.84175 10063.744.03816
10075.1943.7763310086.6844.6702810109.6648.1191310121.1649.0008310155.6348.90058
10167.1350.3676210178.6255.0609510190.1158.67135 10201.659.2330310231.7659.93661
#Mann= 3 , 0 , 0
9840.706    0.12       09840.706    0.12       010231.76    0.12       0
#XS Ineff= 2 , 0
       0                               0
Bank Sta=9840.706,10231.76
Exp/Cntr=0.3,0.1

Type RM Length L Ch R = 1 , 5043.98,130.821700,130.821700,130.821700
XS GIS Cut Line= 4
396301.374871375854732.579965798 396241.47903806854813.309132469
396196.340149164854864.524410246396102.590149158855005.149410265
#Sta/Elev= 30
9866.00351.761329881.46848.678819893.48545.895169910.26743.423549918.82342.89551
 9927.0541.844899931.27541.011219943.83339.844839956.179 40.11029960.61640.53292
9968.77940.234019976.324 39.43829982.10939.151889991.44837.964749995.43836.87893
10006.5740.3545910008.7741.76885 10021.743.2794710034.7943.6632210047.3844.31533
 10059.4 43.877810071.42 44.721810083.4445.9195610095.4647.5831710119.4947.20809
10143.5348.0023510155.5552.5096210167.57 55.167810179.5956.41296 10203.856.45165
#Mann= 3 , 0 , 0
9866.003    0.12       09866.003    0.12       0 10203.8    0.12       0
#XS Ineff= 2 , 0
       0                               0
Bank Sta=9866.003,10203.8
Exp/Cntr=0.3,0.1

Type RM Length L Ch R = 1 ,4913.158,171.704700,171.704700,171.704700
XS GIS Cut Line= 2
396242.477301956854620.687604695396015.914801955854973.118160251
#Sta/Elev= 30
9857.70669.302539862.83368.236359874.72165.277989886.609 62.86779890.02661.89668
9910.38555.436099946.04946.125219963.99742.526999969.82641.183869981.71440.63303
9993.60236.9393310000.9836.3251410005.4936.4701910017.3838.5056510029.2738.59431
10041.1538.4733410053.0440.9393310056.4641.4212810064.9341.5458510167.4141.59905
10171.9242.2014410183.8144.97899 10195.744.81462 10204.4 45.322710207.5945.53022
10222.8947.3535110231.3648.0636410255.1449.1221610267.0350.2958510276.6850.93828
#Mann= 3 , 0 , 0
9857.706  0.0706       09857.706  0.0706       010276.68  0.0706       0
#XS Ineff= 2 , 0
       0                               0
Bank Sta=9857.706,10276.68
Exp/Cntr=0.3,0.1

Type RM Length L Ch R = 1 ,4741.453,134.198400,134.198400,134.198400
XS GIS Cut Line= 3
396102.720357506854546.902882502395982.928690852854730.930660249
395834.491190827854926.243160253
#Sta/Elev= 30
9846.88459.355319868.47754.301059880.40951.919729904.27348.502819928.13745.85467
9934.357 45.37259952.00144.116889971.01743.382349975.86543.000659987.79738.99633
9989.34838.023549999.72933.8058210011.6636.6241910035.5338.5489510047.4640.60011
10112.6241.0351910134.3841.3644910146.9441.31655 10159.541.5275610184.6242.86828
10197.1844.8214910211.7848.39897 10222.350.7463510234.8653.2273210247.4255.35858
10259.9858.7451510277.8963.05362 10285.164.1507810297.6664.2419210311.7864.67829
#Mann= 3 , 0 , 0
9846.884  0.0607       09846.884  0.0607       010311.78  0.0607       0
#XS Ineff= 2 , 0
       0                               0
Bank Sta=9846.884,10311.78
Exp/Cntr=0.3,0.1

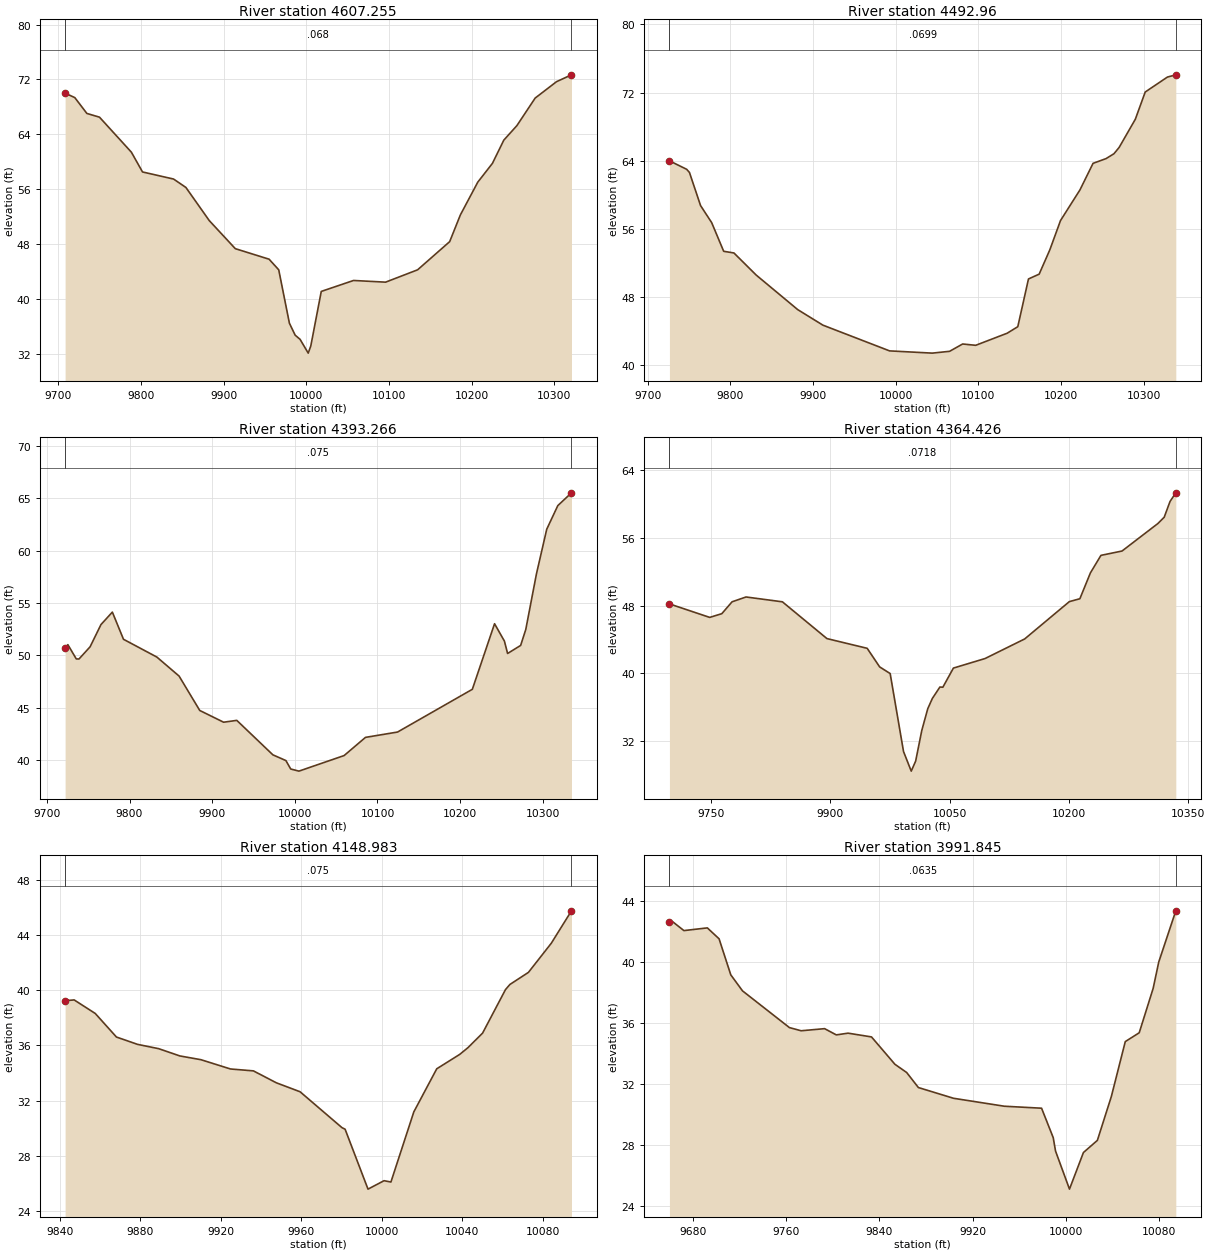
Type RM Length L Ch R = 1 ,4607.255,114.295100,114.295100,114.295100
XS GIS Cut Line= 3
396094.582336666854457.167639411395937.030253328854599.094722755
395683.124003325854908.990556079
#Sta/Elev= 30
9708.03369.988189719.73569.348019734.38967.033619749.61766.492929788.22561.38794
9801.68558.505819839.26257.472829854.20356.24514 9882.4451.418789913.967 47.3242
9954.84545.789839966.50244.24213 9979.4336.455049986.40234.712619992.35834.10396
10002.1832.0976910005.2933.1370910017.9641.09212   10057  42.68810095.7842.44166
10134.5644.2441110173.3548.3510210186.2852.24395 10207.357.0152610225.0659.75873
10238.8663.1488710254.6465.2567310276.7769.2766310302.6371.6661610320.7172.66435
#Mann= 3 , 0 , 0
9708.033   0.068       09708.033   0.068       010320.71   0.068       0
#XS Ineff= 2 , 0
       0                               0
Bank Sta=9708.033,10320.71
Exp/Cntr=0.3,0.1

Type RM Length L Ch R = 1 , 4492.96,99.694400,99.694400,99.694400
XS GIS Cut Line= 3
395992.992885136854401.066628063395835.440893077854542.994105433
395581.534926091854852.890648248
#Sta/Elev= 30
9726.38163.989489747.19962.995929750.59862.627059764.05758.735829777.51656.73009
9792.02153.370429804.43553.172539831.35350.580269881.66746.520379912.10844.69902
9992.73841.6803710044.4541.4175210065.3641.6306810081.14 42.489110096.9242.33417
10134.9443.7513910147.8744.51881 10160.850.1223410173.7350.6889410186.6653.54762
10199.5856.9819510223.1460.5869410238.9263.69209 10254.764.2508810264.2264.82159
10270.48 65.559410290.0868.8690910302.0472.0651410328.8673.8177710339.0674.08308
#Mann= 3 , 0 , 0
9726.381  0.0699       09726.381  0.0699       010339.06  0.0699       0
#XS Ineff= 2 , 0
       0                               0
Bank Sta=9726.381,10339.06
Exp/Cntr=0.3,0.1

Type RM Length L Ch R = 1 ,4393.266,28.839800,28.839800,28.839800
XS GIS Cut Line= 3
395917.472051803854335.962461396395759.920059744854477.889938767
395506.014092758854787.786481582
#Sta/Elev= 30
9722.08350.662359725.41151.020199735.58649.66119 9738.8749.649119752.32950.81694
9765.46852.935619779.24754.127739792.70651.534149833.08449.836239860.00248.02049
9884.99544.739659913.83943.618389929.81843.793049973.45640.505649989.235 39.9566
9995.03939.1527810005.0138.9495410059.6840.4360110085.5342.1701510124.3242.67954
10214.8146.7590510241.6953.01783 10253.651.3623710257.4750.1781910273.2550.94547
10279.4552.4628710292.3857.7742110304.8162.0341510318.2364.2905310334.77 65.5105
#Mann= 3 , 0 , 0
9722.083   0.075       09722.083   0.075       010334.77   0.075       0
#XS Ineff= 2 , 0
       0                               0
Bank Sta=9722.083,10334.77
Exp/Cntr=0.3,0.1

Type RM Length L Ch R = 1 ,4364.426,215.442900,215.442900,215.442900
XS GIS Cut Line= 2
395924.443447798854311.768333883395443.974697769854729.737083878
#Sta/Elev= 30
9697.60448.208469748.23646.611749763.47347.049669776.39248.457079793.94549.02787
9839.65448.45548 9895.68 44.10279946.30742.951239961.95240.753119975.20639.96419
9992.01630.7283910001.7128.4137110007.2529.5992410014.9733.2304210022.4935.80454
10028.2237.0093210037.7238.3674310041.4838.3485910054.7340.6118710094.4941.73953
10144.3844.0606810200.5348.4779910213.7848.8197610227.0451.8813410240.2953.95386
 10266.854.4679710311.9857.7292810319.8258.4677110327.2160.3416510334.4361.35698
#Mann= 3 , 0 , 0
9697.604  0.0718       09697.604  0.0718       010334.43  0.0718       0
#XS Ineff= 2 , 0
       0                               0
Bank Sta=9697.604,10334.43
Exp/Cntr=0.3,0.1

Type RM Length L Ch R = 1 ,4148.983,157.138200,157.138200,157.138200
XS GIS Cut Line= 3
395609.283919168854419.087304845395532.130293693854443.976697963
395450.339375453854593.796282745
#Sta/Elev= 27
9842.59939.241069847.101 39.29689857.60838.312089868.11636.604679878.62336.07272
9889.13135.759499899.63835.233759910.14634.959639924.83434.286819936.22734.14886
9947.62133.283859959.41832.634579980.28730.02594  9981.829.918189993.19325.57002
10001.1626.1808310004.59 26.086510015.9831.1768110027.3734.3000410038.7735.34275
 10042.935.8351110050.1636.8887310061.5540.0456210063.7640.4204210072.9541.29441
10084.3443.4133510094.3645.76101
#Mann= 3 , 0 , 0
9842.599   0.075       09842.599   0.075       010094.36   0.075       0
#XS Ineff= 2 , 0
       0                               0
Bank Sta=9842.599,10094.36
Exp/Cntr=0.3,0.1

Type RM Length L Ch R = 1 ,3991.845,145.479300,145.479300,145.479300
XS GIS Cut Line= 3
 395697.33841306854376.763993601395411.690264944854411.833438032
395288.773598222854493.083438038
#Sta/Elev= 30
9659.50542.608419661.86142.673879671.93642.065519692.086 42.24289702.16141.52713
9712.23639.158829722.31138.107719762.61235.697059772.68735.488399792.83735.62715
9802.91235.217719812.98735.331339833.13735.084939853.28733.286389863.36332.74839
9873.43831.760939903.66331.055289947.29830.534359979.29230.404369989.30928.47038
9991.27927.5937310003.2725.0914610015.2527.4936610027.2428.2928110039.2331.16872
10051.22 34.7777 10063.235.3575910075.1938.2763210079.98 40.003610094.6443.36325
#Mann= 3 , 0 , 0
9659.505  0.0635       09659.505  0.0635       010094.64  0.0635       0
#XS Ineff= 2 , 0
       0                               0
Bank Sta=9659.505,10094.64
Exp/Cntr=0.3,0.1

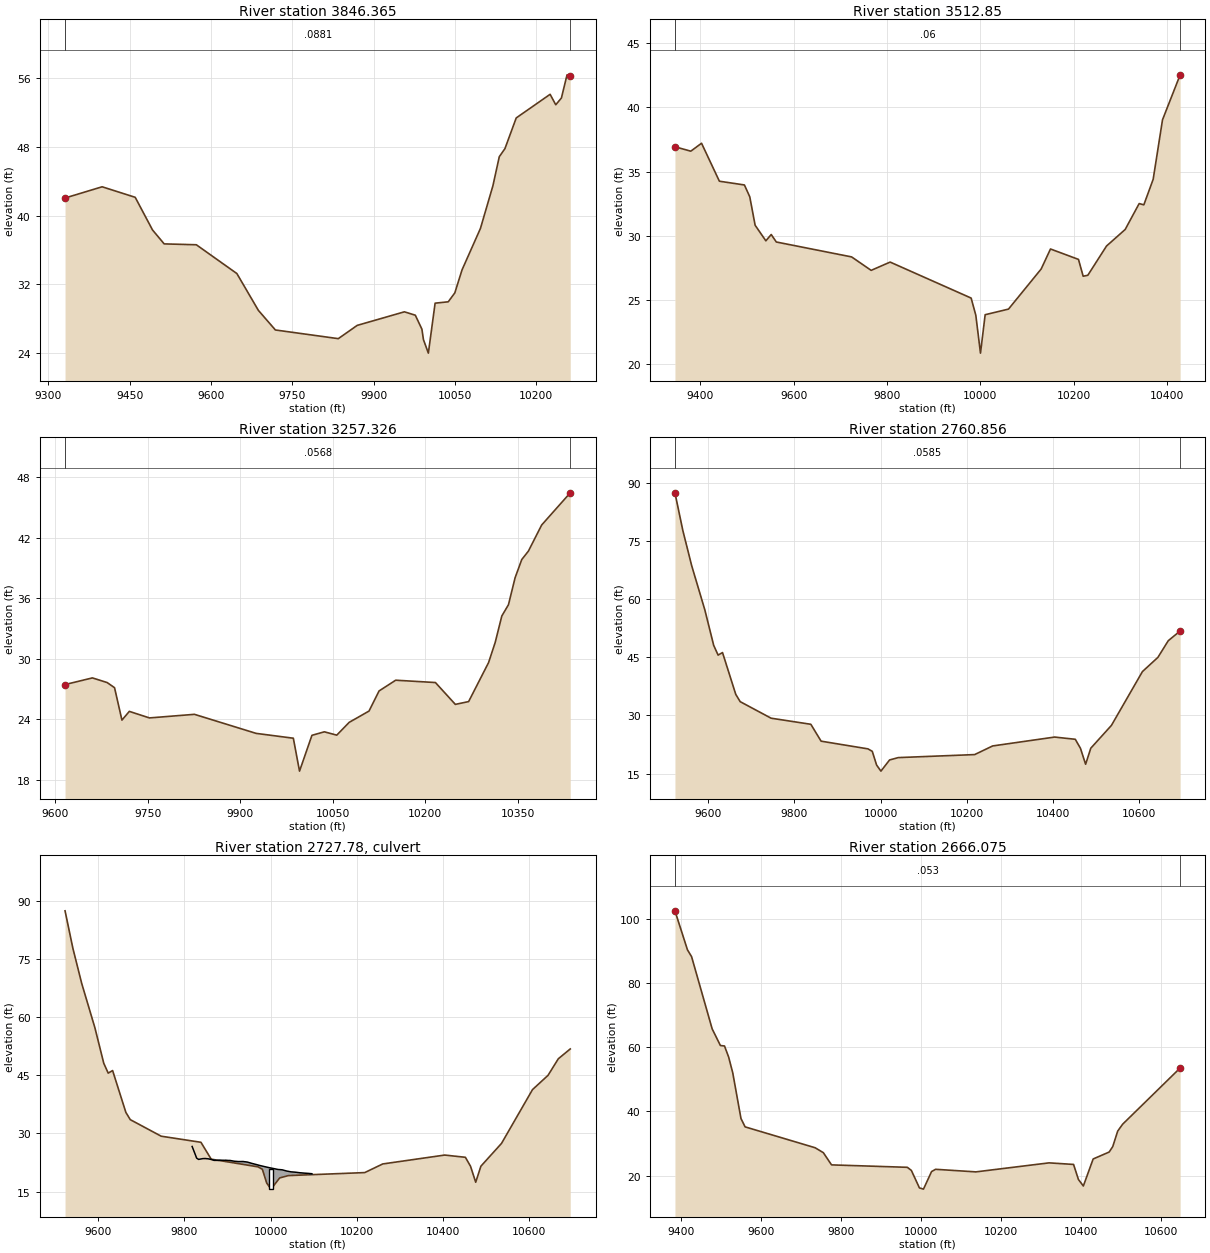
Type RM Length L Ch R = 1 ,3846.365,333.515000,333.515000,333.515000
XS GIS Cut Line= 6
 395527.05231814853772.511705554395481.425199013853906.500323983
395393.984532457854115.787719409395316.287300048854257.841070176
395170.722203735854481.488727528395133.077083581854610.662597564
#Sta/Elev= 30
9330.86742.042329399.27743.350199460.26242.124589492.25638.318119513.71136.70046
9573.04236.59821 9647.8233.245379687.48528.958579718.86426.675569834.84325.66629
9869.74427.210429956.82128.791089976.94128.395389989.10926.769849991.92525.55615
   1000123.9806510013.4529.7978710037.6929.9571510049.8130.9969510063.0833.66729
10097.0238.4929510120.0543.4643210131.8346.8512210142.2547.7929610163.0851.36771
10225.5854.1185910235.9952.9013810246.4153.6842910256.8256.3866910262.7256.23345
#Mann= 3 , 0 , 0
9330.867  0.0881       09330.867  0.0881       010262.72  0.0881       0
#XS Ineff= 2 , 0
       0                               0
Bank Sta=9330.867,10262.72
Exp/Cntr=0.3,0.1

Type RM Length L Ch R = 1 , 3512.85,255.524200,255.524200,255.524200
XS GIS Cut Line= 4
395414.608622578853768.155331925395006.950048126853998.500574172
395011.951089522854412.941131564395017.717449307 854612.77518337
#Sta/Elev= 30
9345.74636.926449379.75436.584239402.72637.20175 9440.9734.247629494.61433.95588
  9506.133.032399517.58630.819369540.55829.612259552.04430.100649562.93529.51897
9724.33328.35823 9766.2127.311629806.865 27.95639980.49325.155839990.49423.82004
10000.4920.87356 10010.523.86162 10060.524.29835 10130.527.4175810150.5128.97488
10210.5128.1645610220.5126.8566110230.5126.9296610270.5329.2032410310.5530.49311
10340.5632.5082910350.5632.4105410370.5734.3987610390.5839.0269910428.3742.52349
#Mann= 3 , 0 , 0
9345.746    0.06       09345.746    0.06       010428.37    0.06       0
#XS Ineff= 2 , 0
       0                10160.01       0
Bank Sta=9345.746,10428.37
Exp/Cntr=0.3,0.1

Type RM Length L Ch R = 1 ,3257.326,496.470200,496.470200,496.470200
XS GIS Cut Line= 6
394952.025913089853929.700914876394820.809895893854016.169897756
394766.556423671854074.763647756394750.036282351854136.951178148
394767.564107566854296.454387082394899.942579718854628.051609338
#Sta/Elev= 30
9616.03227.438659660.374 28.10079684.326 27.63829696.30227.127749708.27823.91212
9720.25424.777889752.87724.129099825.88424.484769925.83422.595959986.19522.11533
9996.25518.8487610016.3822.40218 10036.522.7502210056.6222.4191710076.7423.68758
10108.9424.8108210125.23 26.8069 10152.227.8717610216.6127.6403910248.9125.47276
10270.4525.7497510302.7529.6144810313.5231.6160710324.2834.2448510335.0535.36278
10345.8238.0439910356.5939.8459610367.3540.6802410388.8943.2736510435.2446.46759
#Mann= 3 , 0 , 0
9616.032  0.0568       09616.032  0.0568       010435.24  0.0568       0
#XS Ineff= 2 , 0
       09823.769        10137.82       0
Bank Sta=9616.032,10435.24
Exp/Cntr=0.3,0.1

Type RM Length L Ch R = 1 ,2760.856,94.781300,94.781300,94.781300
XS GIS Cut Line= 6
394197.577128335853947.279039912394135.827942213854267.954198775
394186.226805264854299.690808725394383.705844832854283.519915212
394464.508870961854298.671090986394751.526545377854708.057192982
#Sta/Elev= 30
9522.97587.380529541.125 77.73589561.60968.669689592.33457.195029612.81848.06932
 9623.0645.556239633.30246.210159664.02835.42751 9674.2733.556039745.96329.29227
9838.13127.722259861.91523.372799970.52421.389599980.56920.760799990.61417.22898
10000.6615.6501910020.7518.5296710040.8419.1360310217.9919.91212 10259.822.13909
10403.5424.4291810451.4523.8552910463.4221.53626 10475.417.4226610487.3821.55119
10535.2927.4426910607.1641.3053810643.0944.9732710667.0549.2566810694.6651.78224
#Mann= 3 , 0 , 0
9522.975  0.0585       09522.975  0.0585       010694.66  0.0585       0
#XS Ineff= 2 , 0
       09784.183        10489.87       0
Bank Sta=9522.975,10694.66
Exp/Cntr=0.3,0.1

Type RM Length L Ch R = 2 , 2727.78,,,
Bridge Culvert--1,0,-1,-1, 0
Deck Dist Width WeirC Skew NumUp NumDn MinLoCord MaxHiCord MaxSubmerge Is_Ogee
19.176,56.43,2.6,0,36,36, , , 0.95, 0, 0,0,,
 9817.77 9828.23 9832.70 9841.70 9847.62 9855.17 9862.55 9868.64 9877.48 9882.10
 9892.41 9895.57 9901.84 9905.56 9915.65 9925.74 9935.83 9936.45 9945.92 9956.02
 9966.11 9976.20 9986.29 9996.3810006.4710010.7910016.5710026.6610036.7510046.84
10056.9310067.0210077.1210085.1410087.2110095.44
   26.64   23.63   23.31   23.50   23.54   23.46   23.28   23.06   23.06   23.11
   23.08   23.10   23.04   23.04   22.84   22.75   22.77   22.76   22.62   22.29
   22.00   21.70   21.44   21.18   20.96   20.86   20.72   20.63   20.32   20.11
   20.02   19.88   19.78   19.72   19.70   19.62
                                                                                
                                                                                
                                                                                
                                                
 9817.77 9828.23 9832.70 9841.70 9847.62 9855.17 9862.55 9868.64 9877.48 9882.10
 9892.41 9895.57 9901.84 9905.56 9915.65 9925.74 9935.83 9936.45 9945.92 9956.02
 9966.11 9976.20 9986.29 9996.3810006.4710010.7910016.5710026.6610036.7510046.84
10056.9310067.0210077.1210085.1410087.2110095.44
   26.64   23.63   23.31   23.50   23.54   23.46   23.28   23.06   23.06   23.11
   23.08   23.10   23.04   23.04   22.84   22.75   22.77   22.76   22.62   22.29
   22.00   21.70   21.44   21.18   20.96   20.86   20.72   20.63   20.32   20.11
   20.02   19.88   19.78   19.72   19.70   19.62
                                                                                
                                                                                
                                                                                
                                                
BR Coef=-1 , 0 , 0 ,, 0 ,,,0.8,-1,,0,
WSPro=,,,, 1 ,,,, 0 ,,,, 0 ,,,,-1 ,-1 ,-1 , 0 , 0 , 0 , 0 , 0
Culvert=2,5,10,56.43,0.013,0.4,1,8,2,15.744,10000,15.365,10000,Culvert #1, 0, 19.176
Culvert Bottom n=0.013
BC Design=,, 0 ,, 0 ,,,,,,

Type RM Length L Ch R = 1 ,2666.075,174.119300,174.119300,174.119300
XS GIS Cut Line= 6
394185.532857532853924.601088578394092.216885277854303.290324691
394106.992805366 854380.58404388394371.740249815854367.033037333
394452.564549635854383.081629871394707.855666527854742.428769262
#Sta/Elev= 30
9383.725102.43129415.03390.287199425.33288.163269476.82865.672459497.42660.49627
9507.72560.343199518.02556.917149528.32451.990679548.92237.755249559.22135.16476
9734.30628.671829754.90527.138629775.48323.329559965.12322.571689975.21821.60136
 9995.4116.1555810005.51 15.7807 10025.721.2453110035.7921.9540810136.6521.15014
10319.6223.9569410380.9523.4696610393.22 18.773110405.4816.7608610430.0225.16799
10470.0727.3311210479.0829.0392610491.3533.8286210503.6235.9729710647.66  53.498
#Mann= 3 , 0 , 0
9383.725   0.053       09383.725   0.053       010647.66   0.053       0
#XS Ineff= 2 , 0
       09685.308        10452.43       0
Bank Sta=9383.725,10647.66
Exp/Cntr=0.3,0.1

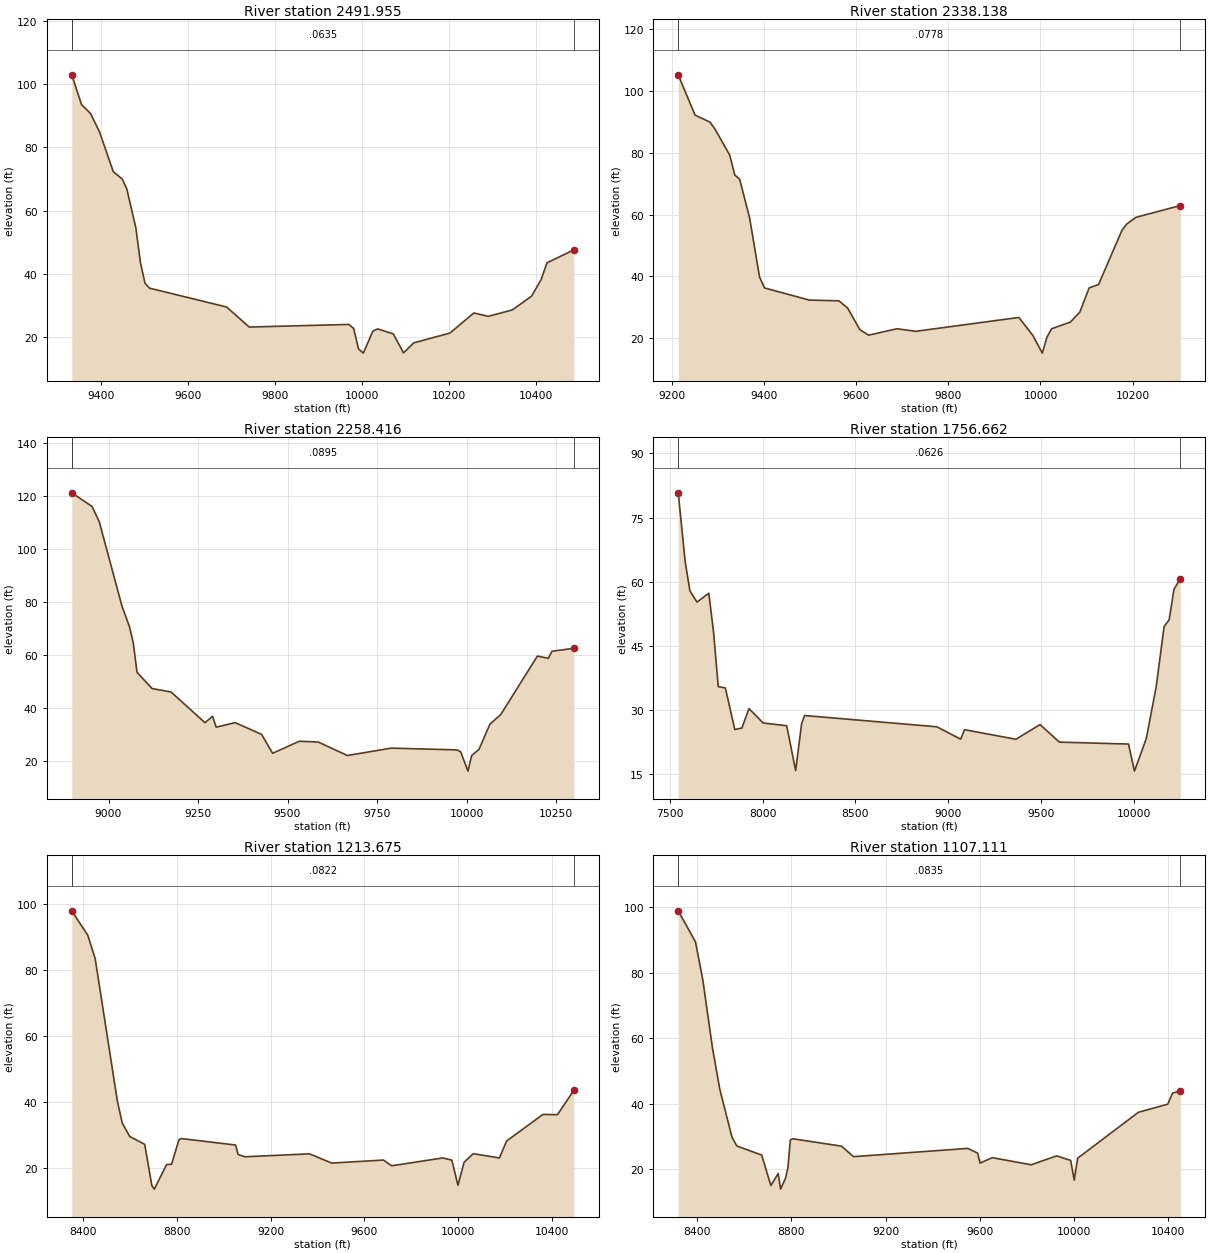
Type RM Length L Ch R = 1 ,2491.955,153.817700,153.817700,153.817700
XS GIS Cut Line= 5
394176.472048502 853923.56621153 394064.66649298854302.038433723
394104.597048496854506.899544831394207.027604055854555.510655958
394603.124165586854741.214273766
#Sta/Elev= 30
9333.386102.89679355.73693.52926 9376.5990.677149397.44584.797539428.726 72.3323
9449.58169.967219460.00866.822589480.862 54.4708 9491.2943.555939501.71737.08107
9512.14435.519759689.40729.571219741.23323.240049970.39724.064559981.46622.80039
9992.53516.34677 10003.6 15.003210025.7421.9931610036.81  22.64710072.4821.08835
10096.0415.0904310119.59 18.250310202.5121.3270110257.7327.6873110290.8626.62784
10346.0928.6352910390.2632.9770110412.3538.2025710425.8443.5236210487.5947.60999
#Mann= 3 , 0 , 0
9333.386  0.0635       09333.386  0.0635       010487.59  0.0635       0
#XS Ineff= 2 , 0
       09658.331                       0
Bank Sta=9333.386,10487.59
Exp/Cntr=0.3,0.1

Type RM Length L Ch R = 1 ,2338.138,79.721600,79.721600,79.721600
XS GIS Cut Line= 3
   394171.553067853911.124081878394015.303066997854301.749081874
394140.090317321854959.409716015
#Sta/Elev= 30
9213.493105.28889249.97892.236339282.28989.97614 9293.0687.759779325.37179.25403
9336.141 72.84669346.911 71.42069368.45258.933089389.99339.806919400.76336.22254
9497.69632.291199562.31832.037579581.17329.729649608.09922.64519 9626.94 20.9058
 9688.4122.985639729.124 22.15899953.04926.648149983.58420.7967610003.9415.08641
10014.1220.30885 10024.3 22.995410065.01 25.157910085.3728.3617410105.7336.23812
10126.0837.3170610176.97 54.913110187.1556.9139110207.5159.11753 10303.662.91644
#Mann= 3 , 0 , 0
9213.493  0.0778       09213.493  0.0778       0 10303.6  0.0778       0
#XS Ineff= 2 , 0
       09599.747                       0
Bank Sta=9213.493,10303.6
Exp/Cntr=0.3,0.1

Type RM Length L Ch R = 1 ,2258.416,501.754100,501.754100,501.754100
XS GIS Cut Line= 3
394142.966713226853632.175276627393926.761400344854278.311581887
394069.433721315854984.795324239
#Sta/Elev= 30
8897.387121.30048954.008116.16348974.181110.35739037.45178.530599058.54170.68538
9069.08664.636259079.63153.444219121.81147.308839174.53646.03354 9269.4434.41016
 9290.53 36.83849300.66232.71931  9353.834.431829427.61529.975019458.23222.84501
9533.06527.40313 9585.5627.102929667.17522.010259789.59824.795729973.23124.12747
9983.43323.3955910003.8416.1019110014.0421.9944410034.4424.3019310065.0533.83325
10095.6537.5304210197.6759.5961610228.2858.7404210238.4861.4120710299.4862.54655
#Mann= 3 , 0 , 0
8897.387  0.0895       08897.387  0.0895       010299.48  0.0895       0
#XS Ineff= 2 , 0
       09627.414                       0
Bank Sta=8897.387,10299.48
Exp/Cntr=0.3,0.1

Type RM Length L Ch R = 1 ,1756.662,542.987300,542.987300,542.987300
XS GIS Cut Line= 3
392362.334072769852765.638414875393127.959072769 853734.38841489
393635.771572769855117.200914875
#Sta/Elev= 30
7544.00380.762627581.42764.706097606.91957.873667645.15755.245567708.88757.31599
 7734.3848.268427759.87235.50595 7798.1135.193287849.09425.481767887.33225.83796
 7925.5730.376058002.04627.005358128.89726.370788177.27915.890578209.53526.86037
8225.662 28.7495 8939.2226.116539067.05523.227569088.36125.443079365.33923.20365
9495.41126.638799599.70422.538939972.55822.0881910004.5215.7637410068.4423.38669
 10121.735.4309110164.3149.5031910191.6251.0889410217.5858.2031510251.8860.73033
#Mann= 3 , 0 , 0
7544.003  0.0626       07544.003  0.0626       010251.88  0.0626       0
#XS Ineff= 2 , 0
       09478.339                       0
Bank Sta=7544.003,10251.88
Exp/Cntr=0.3,0.1

Type RM Length L Ch R = 1 ,1213.675,106.563600,106.563600,106.563600
XS GIS Cut Line= 4
392500.446858734853429.997899771392963.988525391854881.386788651
393172.321858764855131.386788636393243.502414286855412.636788636
#Sta/Elev= 30
8353.18397.927888421.41990.547948452.91283.483788547.39140.383638568.38633.72778
8599.87929.681588663.96927.291838694.35814.820418704.85513.738778757.34321.18972
8778.33921.273778809.83228.658588820.32929.037059051.27727.075119061.77524.21738
9091.26623.527689366.20624.411659460.68521.618459681.135 22.53469715.77720.79533
9933.56923.16503 9972.6222.504449998.65414.8938710024.6921.8621810063.7424.45917
10175.1723.1656210205.9528.2993710360.6836.3427410422.5736.2565810492.3443.65056
#Mann= 3 , 0 , 0
8353.183  0.0822       08353.183  0.0822       010492.34  0.0822       0
#XS Ineff= 2 , 0
       09042.512                       0
Bank Sta=8353.183,10492.34
Exp/Cntr=0.3,0.1

Type RM Length L Ch R = 1 ,1107.111,248.607700,248.607700,248.607700
XS GIS Cut Line= 4
392486.905192077853434.164566442392875.446858764 854947.35901086
393083.780192047855176.525677547393151.488525391855426.525677547
#Sta/Elev= 30
8319.76698.867338392.89989.419528423.87277.90945 8465.1757.010798496.14344.46343
8547.76529.864058568.41427.148078673.98524.368268712.95515.057078743.928 18.7289
8754.25313.977988774.90217.271958785.22620.50509 8795.5528.972218805.87529.34182
9012.36327.091419063.98523.885319549.23126.404729590.52824.936899600.85321.92152
9652.475 23.57599817.665 21.41099925.98124.121099985.44522.7386410000.4916.74043
10015.1823.4167510273.0637.4226310397.3839.89095 10418.143.3115510450.7643.82518
#Mann= 3 , 0 , 0
8319.766  0.0835       08319.766  0.0835       010450.76  0.0835       0
#XS Ineff= 2 , 0
       09011.544                       0
Bank Sta=8319.766,10450.76
Exp/Cntr=0.3,0.1

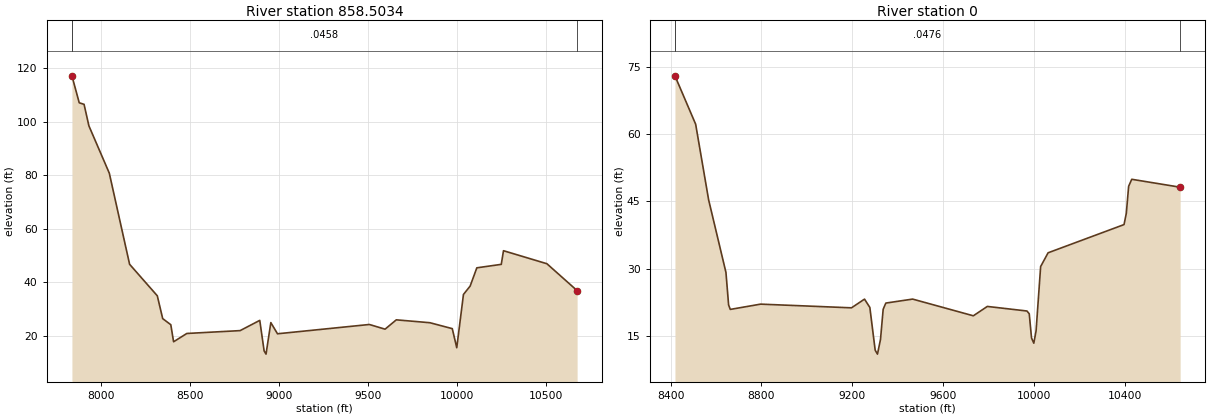
Type RM Length L Ch R = 1 ,858.5034,858.503400,858.503400,858.503400
XS GIS Cut Line= 6
391364.727844123853451.722665454391600.277210649853676.242332896
391813.037371672853916.005441212392171.029420362854402.575436084
392768.739354316 855185.03512839393124.892061629855668.142895567
#Sta/Elev= 30
7838.831117.09137879.834107.02227906.924106.44657934.06598.415248048.57280.73888
8162.51746.704068317.93234.934368348.25726.411488393.74624.125658409.35517.76349
8483.65820.86046 8782.7921.929038892.96925.754318917.45314.348988928.07313.14657
8955.11724.918488992.48720.746759507.995 24.21649596.19922.469729659.202 25.9524
9847.86724.875959973.33722.66646 9998.4315.5288910036.0735.4344610073.7138.57651
10111.1245.3789410248.2646.6731910260.7351.7704310504.5246.9065210673.9636.86836
#Mann= 3 , 0 , 0
7838.831  0.0458       07838.831  0.0458       010673.96  0.0458       0
#XS Ineff= 2 , 0
       08958.945                       0
Bank Sta=7838.831,10673.96
Exp/Cntr=0.3,0.1

Type RM Length L Ch R = 1 ,       0,0.000000,0.000000,0.000000
XS GIS Cut Line= 6
391247.173681009853813.643205634391755.469111574854639.354945946
391888.781245553855193.509687356391893.268008172855233.772356902
391896.702403394 855269.08530821392498.900913056855370.383785274
#Sta/Elev= 30
8418.90372.937428510.13662.157118567.36445.29125 8643.6129.135318655.35321.89153
8662.74320.893638796.26722.068999196.86921.247549254.23823.186359277.72421.33346
 9301.2111.816319311.32510.931589324.69514.215649336.43820.931539348.18122.30616
9466.32723.191589733.74419.472669795.45621.55684 9970.0520.538119980.11119.91589
9990.17314.5407610000.2313.3701210010.2816.1242210030.3830.4467910063.1833.50674
10397.8139.7924510407.9642.32494 10418.148.3210610431.8449.8854410645.1448.12237
#Mann= 3 , 0 , 0
8418.903  0.0476       08418.903  0.0476       010645.14  0.0476       0
#XS Ineff= 2 , 0
       09157.841                       0
Bank Sta=8418.903,10645.14
Exp/Cntr=0.3,0.1